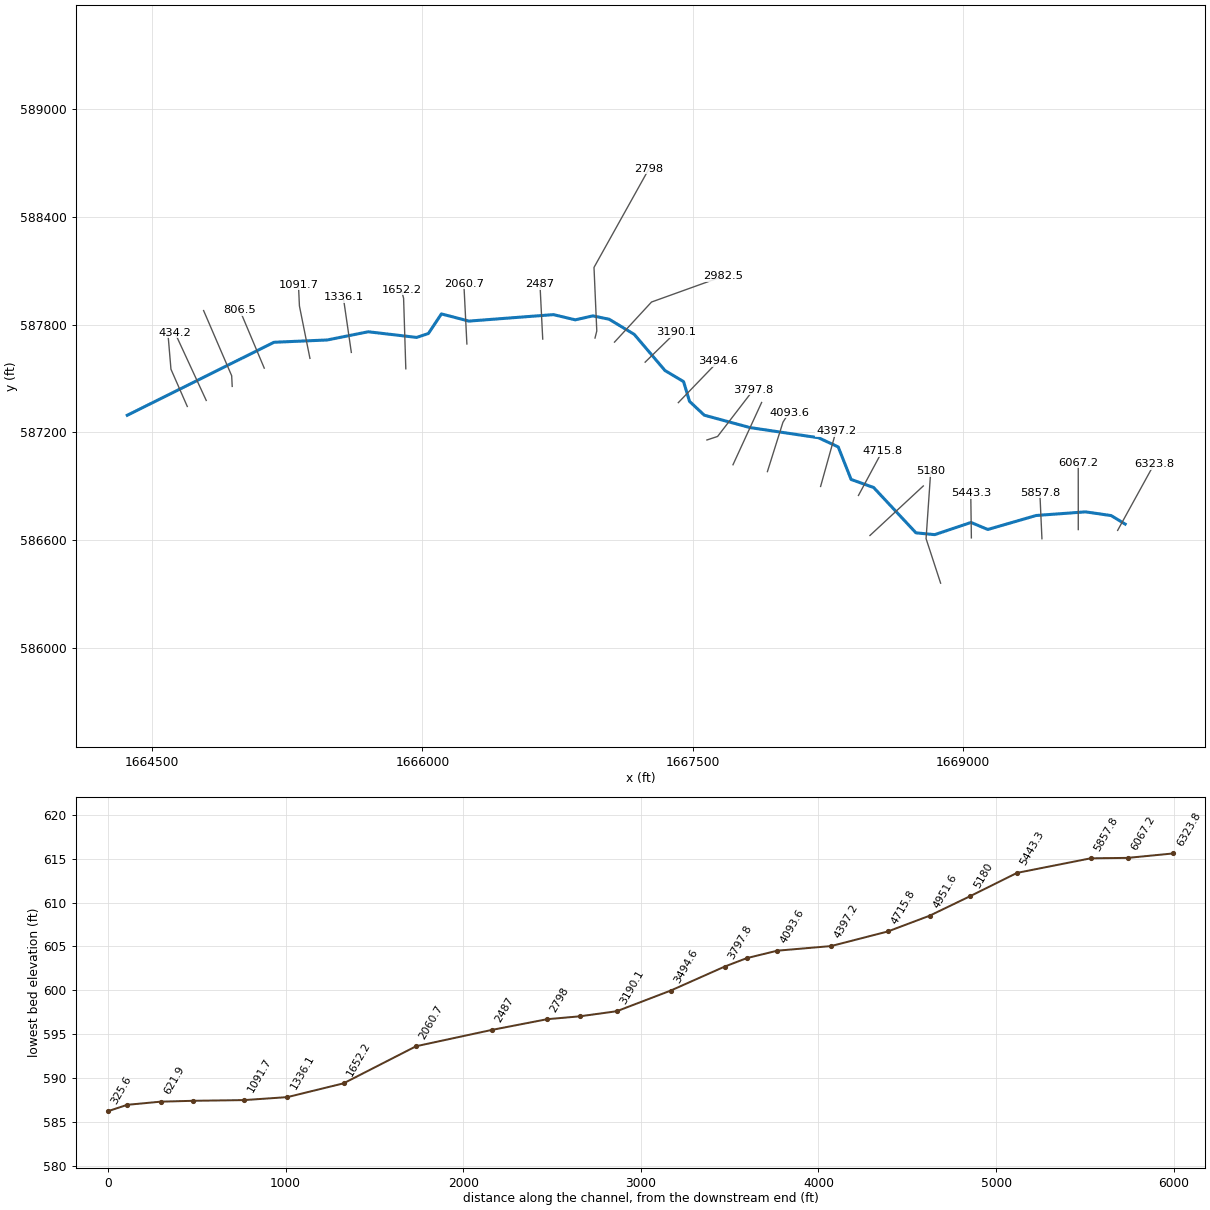
--- NP6.prj (project) ---

Proj Title=NP6
Current Plan=p01
Default Exp/Contr=0,0
English Units
Geom File=g01
Flow File=f01
Plan File=p01
BEGIN DESCRIPTION:
AMEC Environment & Infrastructure, 2013
Projection: NAD 1983 State Plane West Virginia South FIPS 4702 (US Feet)
Vertical Datum: NAVD 1988
END DESCRIPTION:
DSS Export Rating Curves= 0
DSS Export Rating Curve Sorted= 0
DSS Export Volume Flow Curves= 0
DXF OffsetX= 0
DXF OffsetY= 0
DXF ScaleX= 0
DXF ScaleY= 0

--- NP6.p01 (plan) ---

Plan Title=Floodplain
Program Version=4.00
Geom File=g01
Flow File=f01
K Sum by GR=0
Std Step Tol=0.01
Critical Tol=0.01
Num of Std Step Trials=20
Max Error Tol=0.3
Flow Tol Ratio=0.001
Split Flow NTrial=30
Split Flow Tol=0.02
Split Flow Ratio=0.02
Log Output Level=0
Friction Slope Method=1
Unsteady Friction Slope Method=2
Unsteady Bridges Friction Slope Method=1
Global Log Level=0
CheckData=False
Run HTab=0
Run UNet=0
Run PostProcess=0
UNET Theta=0
UNET Theta Warmup=0
UNET ZTol=0
UNET ZSATol=0
UNET MxIter=0
UNET MaxInSteps=0
UNET DtIC=0
UNET DtMin=0
UNET MaxCRTS=0
UNET WFStab=0
UNET SFStab=0
UNET WFX=0
UNET SFX=0
UNET DSS MLevel=0
UNET DZMax Abort=0
UNET Convert EG Bridges=0
UNET Use Existing IB Tables=0
UNET Froude Limit=0
UNET Froude Power=0
Write IC File=0
Echo Input=False
Echo Output=False
Write Detailed=0

--- NP6.f01 (steady flow) ---

Flow Title=USGS Regress. Eqn. (2010) - Western-Plateaus
Program Version=4.10
Number of Profiles= 1
Profile Names=P100yr
River Rch & RM=NP6,Main            ,6323.8
     834
River Rch & RM=NP6,Main            ,5857.8
     925
River Rch & RM=NP6,Main            ,5180
     938
River Rch & RM=NP6,Main            ,2982.5
     997
River Rch & RM=NP6,Main            ,1652.2
    1001
River Rch & RM=NP6,Main            ,1336.1
    1274
River Rch & RM=NP6,Main            ,806.5
    1278
Boundary for River Rch & Prof#=NP6,Main            , 1
Up Type= 0
Dn Type= 3
Dn Slope=0.00772
DSS Import GetInterval= 0
DSS Import GetPeak= 0
DSS Import FillOption= 0

--- NP6.g01 (geometry) ---

Geom Title=USGS 3m DEM
Program Version=4.10

River Reach=NP6             ,Main
Reach XY= 30
     1669902.731      586689.854     1669825.127       586737.25
     1669682.621      586757.918      1669408.46      586737.771
     1669139.949      586659.874      1669046.72      586698.936
     1668845.157      586631.228      1668740.99      586641.124
     1668505.834       586893.48     1668380.834      586938.272
     1668309.133      587119.392     1668199.541       587170.39
     1667819.007      587227.031     1667565.489      587295.881
      1667483.54      587372.748     1667450.276      587483.026
     1667347.411      587544.224     1667176.464      587745.735
     1667036.981       587829.93     1666946.588      587848.622
     1666849.001      587826.614     1666727.797      587855.549
     1666258.362      587819.603     1666105.584      587859.534
     1666033.362      587750.506     1665967.902      587728.686
     1665699.392       587760.17     1665472.013       587714.58
      1665175.92      587701.733     1664361.007      587295.437

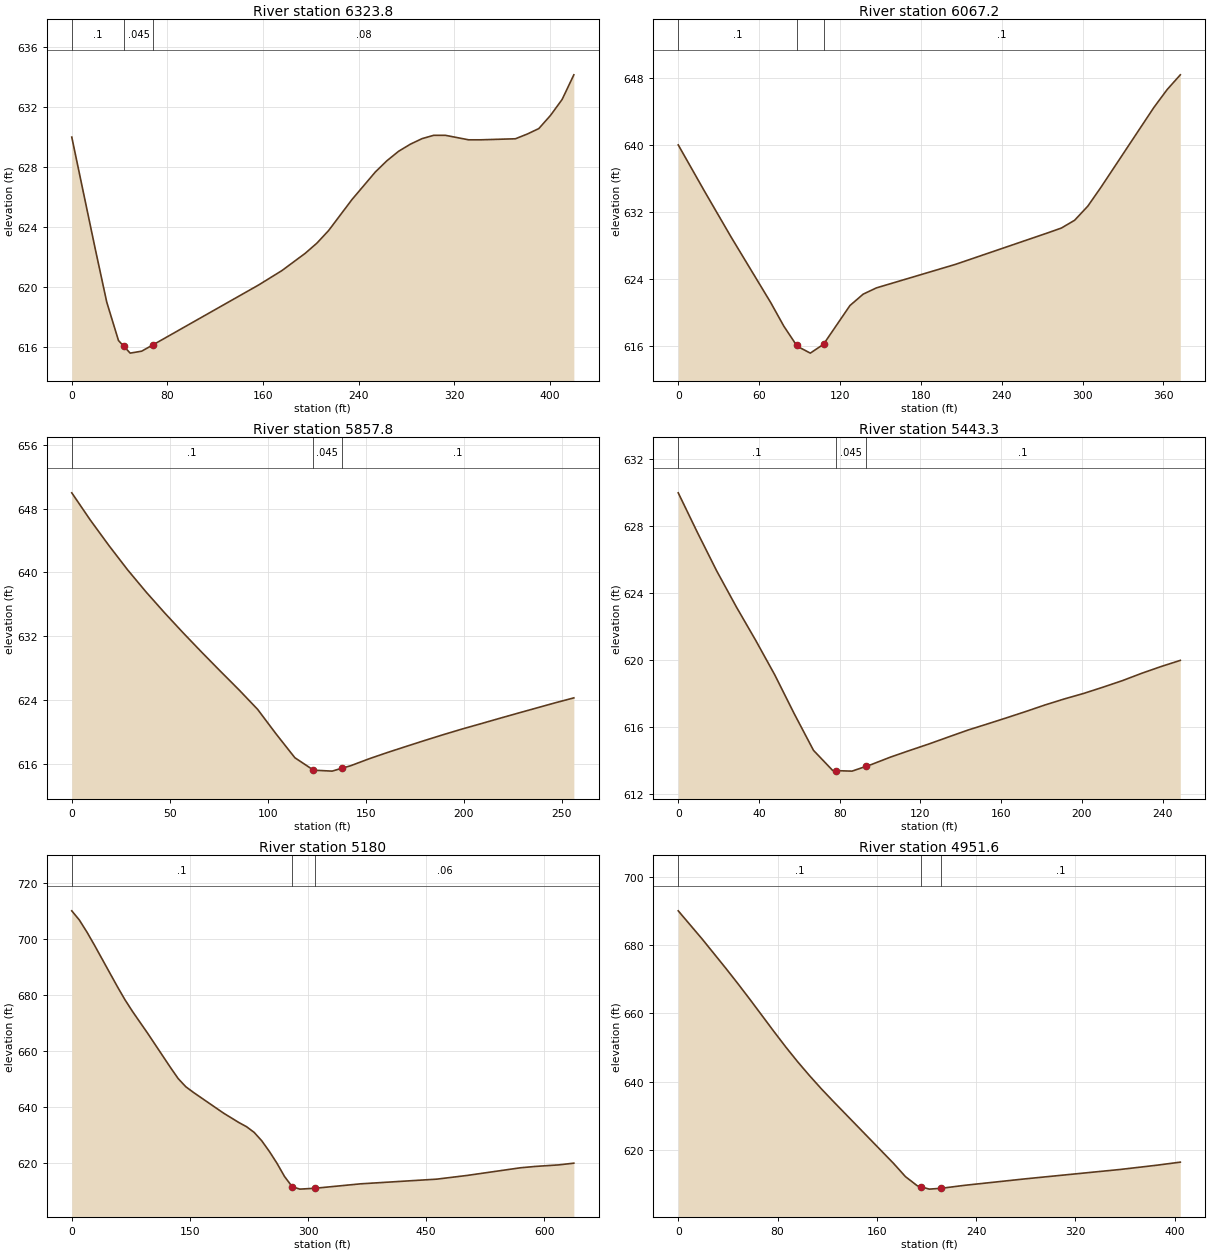
Type RM Length L Ch R = 1 ,6323.8  ,244.9,256.6,267.7
XS GIS Cut Line= 2
     1669860.977      586654.848     1670063.255       587023.15
#Sta/Elev= 29
       0     630    19.5  622.61    29.3     619    39.1  616.45    43.5  616.07
    48.9  615.61    58.5  615.74    68.4  616.18   156.4  620.15   175.9  621.11
   195.4  622.26   205.2  622.94     215  623.78   234.5  625.84   254.1  627.68
   263.8  628.43   273.6  629.06   283.4  629.53   293.2   629.9   302.9  630.12
   312.7  630.12   332.2  629.82     342  629.82   371.3  629.89   381.1   630.2
   390.9  630.57   400.6  631.44   410.4  632.51   420.2  634.15
#Mann= 3 , 0 , 0
       0      .1       0    43.5    .045       0    68.4     .08       0
Bank Sta=43.5,68.4
XS Rating Curve= 0 ,0
Exp/Cntr=0.3,0.1

Type RM Length L Ch R = 1 ,6067.2  ,208.3,209.5,210.4
XS GIS Cut Line= 2
     1669642.293       586659.31     1669642.141      587031.788
#Sta/Elev= 21
       0     640    19.6  634.43    39.2  628.99    68.6  621.15    78.4  618.31
    87.8  616.03    88.2  615.93      98   615.1   107.8  616.16   127.4  620.79
   137.2  622.15     147   622.9   205.8  625.72   274.5   629.5   284.3  630.06
   294.1  630.99   303.9  632.68   313.7  634.95   352.9  644.48   362.7  646.61
   372.5  648.38
#Mann= 3 , 0 , 0
       0      .1       0    87.8    .045       0   107.8      .1       0
Bank Sta=87.8,107.8
XS Rating Curve= 0 ,0
Exp/Cntr=0.3,0.1

Type RM Length L Ch R = 1 ,5857.8  ,411,414.4,411.5
XS GIS Cut Line= 2
     1669440.531      586608.416     1669428.962      586864.413
#Sta/Elev= 30
       0     650     9.5  646.57      19  643.37    28.5  640.33      38  637.53
    47.5   634.9      57  632.38    66.4  629.97    75.9  627.59    85.4  625.25
    94.9   622.8   104.4  619.69   113.9  616.73     123  615.24   123.4  615.17
   132.9  615.05     138  615.42   142.4  615.73   151.9  616.61   161.4  617.41
   170.8  618.16   180.3  618.91   189.8  619.64   199.3  620.34   208.8     621
   218.3  621.67   227.8  622.33   237.3  622.98   246.8  623.63   256.3  624.25
#Mann= 3 , 0 , 0
       0      .1       0     123    .045       0     138      .1       0
Bank Sta=123,138
XS Rating Curve= 0 ,0
Exp/Cntr=0.3,0.1

Type RM Length L Ch R = 1 ,5443.3  ,264.5,263.3,261.8
XS GIS Cut Line= 2
     1669048.681       586613.16     1669045.206      586861.833
#Sta/Elev= 29
       0     630     9.6  627.61    19.1  625.33    28.7  623.21    38.3  621.21
    47.8  619.14    57.4  616.83      67  614.63    76.5  613.43    77.9  613.42
    86.1  613.39    92.9  613.67    95.6  613.78   105.2  614.23   114.8  614.63
   124.4  615.02   133.9  615.43   143.5  615.84     153   616.2   162.6  616.57
   172.2  616.95   181.7  617.34   191.3   617.7   200.9  618.03   210.4   618.4
     220  618.79   229.6  619.23   239.1  619.63   248.7     620
#Mann= 3 , 0 , 0
       0      .1       0    77.9    .045       0    92.9      .1       0
Bank Sta=77.9,92.9
XS Rating Curve= 0 ,0
Exp/Cntr=0.3,0.1

Type RM Length L Ch R = 1 ,5180    ,246.5,228.5,208.1
XS GIS Cut Line= 3
     1668877.884      586361.123     1668797.073      586608.863
     1668823.021         586985.
#Sta/Elev= 30
       0     710     9.6  706.73    19.3  702.41      29  697.66    57.9  682.97
    67.6  678.27    77.2  674.09    96.5  666.27   125.5  654.06   135.1  650.18
   144.8  647.26   154.4  645.26     193   637.8   212.3  634.48     222     633
   231.6  630.98   241.3  627.97   250.9   624.2   260.6  619.96   270.2  615.24
   279.9  611.61   289.6  610.74   308.9  611.05   366.9  612.63   463.6   614.3
   502.3  615.63     570  618.36   589.3  618.85   618.3  619.38   637.6     620
#Mann= 3 , 0 , 0
       0      .1       0   279.9    .045       0   308.9     .06       0
Bank Sta=279.9,308.9
XS Rating Curve= 0 ,0
Exp/Cntr=0.3,0.1

Type RM Length L Ch R = 1 ,4951.6  ,228.3,235.8,243.1
XS GIS Cut Line= 2
      1668485.41      586626.477      1668781.66      586902.114
#Sta/Elev= 22
       0     690    19.3  681.74    38.5  673.11    48.2  668.62    57.8  664.06
    77.1  654.67    86.7  650.11    96.3  645.78     106  641.66   115.6  637.78
   125.2  634.11   173.4  616.09   183.1  612.17   192.7  609.48   195.9  609.16
   202.3  608.51     212  608.76   231.2  609.64   279.4  611.51   356.5  614.28
   385.4   615.5   404.6  616.41
#Mann= 3 , 0 , 0
       0      .1       0   195.9    .045       0     212      .1       0
Bank Sta=195.9,212
XS Rating Curve= 0 ,0
Exp/Cntr=0.3,0.1

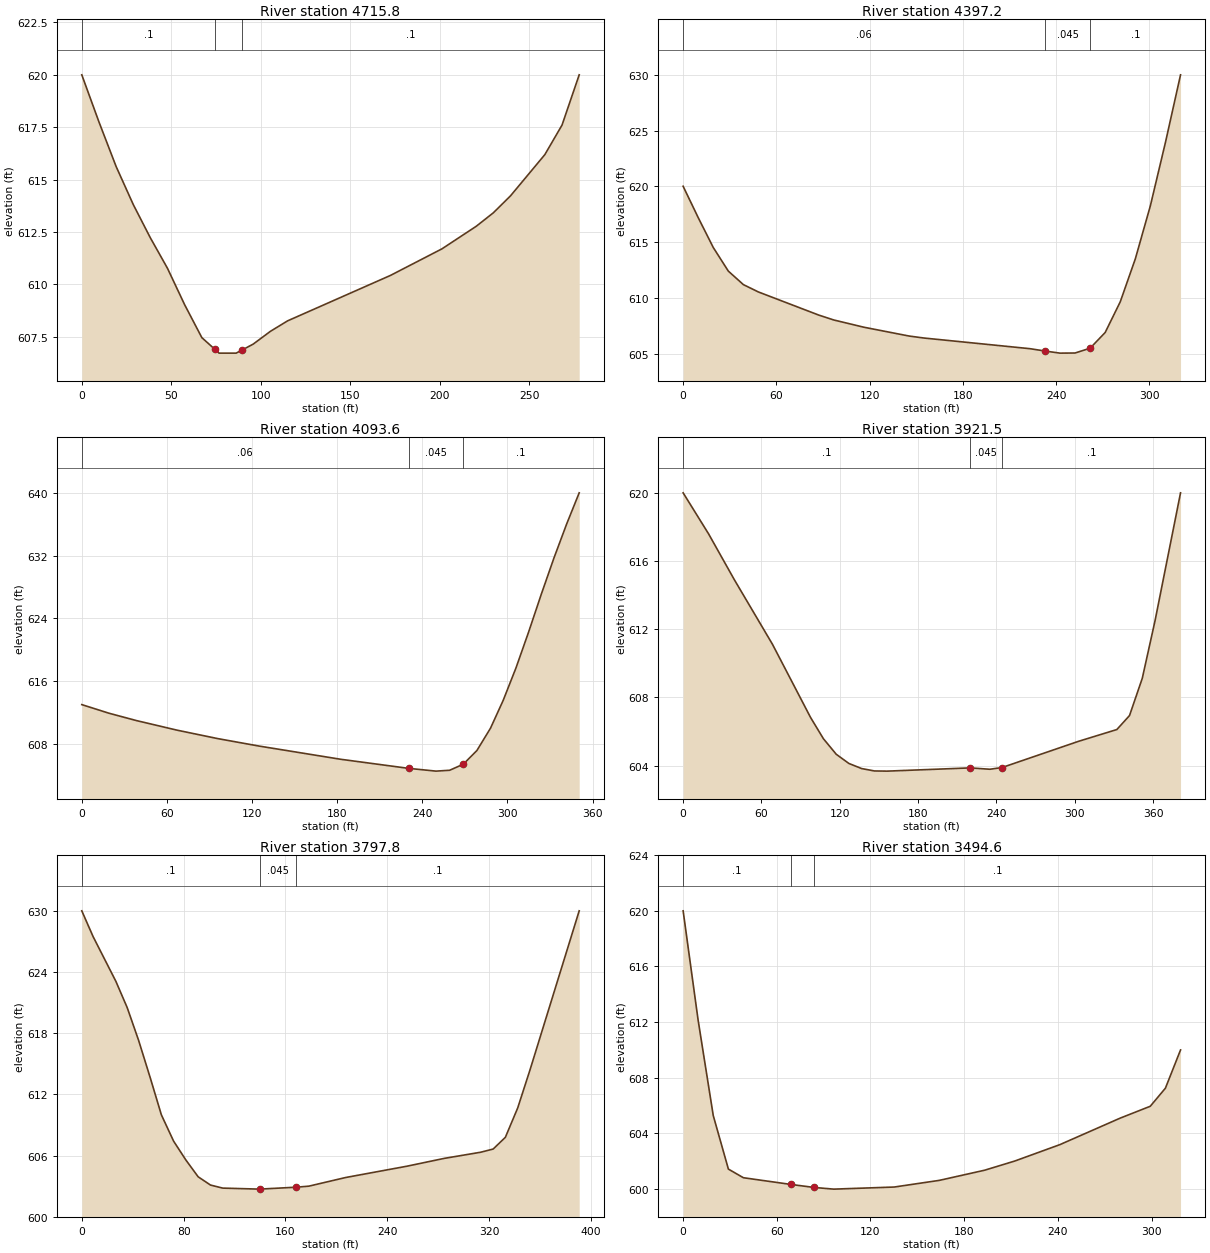
Type RM Length L Ch R = 1 ,4715.8  ,313.6,318.5,323.1
XS GIS Cut Line= 2
     1668421.554       586849.28     1668553.081      587094.171
#Sta/Elev= 23
       0     620     9.6  617.75    19.2  615.62    28.8   613.8    38.3  612.22
    47.9  610.76    57.5  609.02    67.1  607.45    74.4  606.89    76.7  606.71
    86.3  606.71    89.4  606.85    95.8  607.14   105.4  607.75     115  608.25
   172.5  610.42   201.3  611.69   220.5  612.77     230  613.41   239.6  614.22
   258.8  616.19   268.4   617.6     278     620
#Mann= 3 , 0 , 0
       0      .1       0    74.4    .045       0    89.4      .1       0
Bank Sta=74.4,89.4
XS Rating Curve= 0 ,0
Exp/Cntr=0.3,0.1

Type RM Length L Ch R = 1 ,4397.2  ,304.7,303.6,302.5
XS GIS Cut Line= 2
     1668211.345      586899.317     1668297.176      587207.727
#Sta/Elev= 22
       0  620.01     9.7   617.2    19.4  614.52    29.1   612.4    38.8  611.19
    48.5  610.53    87.3  608.46      97  608.02   116.4  607.37   145.5  606.58
   155.2   606.4   223.1  605.45   232.8  605.24   242.5  605.05   252.2  605.06
   261.9  605.49   271.6   606.9   281.3  609.65     291   613.5   300.7  618.27
   310.4  623.95   320.1     630
#Mann= 3 , 0 , 0
       0     .06       0   232.8    .045       0   261.9      .1       0
Bank Sta=232.8,261.9
XS Rating Curve= 0 ,0
Exp/Cntr=0.3,0.1

Type RM Length L Ch R = 1 ,4093.6  ,175,172.1,169
XS GIS Cut Line= 3
     1667915.984      586981.903     1668002.279      587256.774
     1668035.547      587309.728
#Sta/Elev= 20
       0     613    19.2   611.9    38.4  610.97    67.2  609.74      96  608.66
   124.8  607.72   182.5  606.03   230.5  604.87   249.7  604.52   259.3  604.63
   268.9   605.4   278.5  607.15   288.1     610     297  613.53     306  617.66
   314.9  622.23   323.8  627.03   332.8  631.69   341.7     636   350.6     640
#Mann= 3 , 0 , 0
       0     .06       0   230.5    .045       0   268.9      .1       0
Bank Sta=230.5,268.9
XS Rating Curve= 0 ,0
Exp/Cntr=0.3,0.1

Type RM Length L Ch R = 1 ,3921.5  ,129.3,123.7,118.4
XS GIS Cut Line= 2
     1667724.834      587020.177     1667883.791      587366.586
#Sta/Elev= 20
       0     620    19.6  617.58    39.1  614.92    68.4  611.12    97.7  606.81
   107.5  605.57   117.3  604.66     127  604.12   136.8  603.82   146.6  603.68
   156.4  603.67     220  603.86     235  603.78   244.3  603.88     303  605.42
   332.3  606.11     342  606.93   351.8  609.12   361.6  612.51   381.1     620
#Mann= 3 , 0 , 0
       0      .1       0     220    .045       0   244.3      .1       0
Bank Sta=220,244.3
XS Rating Curve= 0 ,0
Exp/Cntr=0.3,0.1

Type RM Length L Ch R = 1 ,3797.8  ,300.1,303.2,305.1
XS GIS Cut Line= 3
     1667580.098      587157.972     1667639.387      587177.657
     1667839.101      587438.085
#Sta/Elev= 24
       0     630     8.9  627.47    26.8  623.08    35.7   620.5    44.6  617.31
    53.6   613.7    62.5     610    72.1  607.42    81.8  605.56    91.4  603.92
   101.1  603.11   110.7  602.81   139.7  602.71   168.6   602.9   178.3     603
   207.3  603.85   255.5  604.96   284.5  605.72   313.4  606.33   323.1  606.64
   332.7  607.79   342.4  610.67     352  614.38   390.7     630
#Mann= 3 , 0 , 0
       0      .1       0   139.7    .045       0   168.6      .1       0
Bank Sta=139.7,168.6
XS Rating Curve= 0 ,0
Exp/Cntr=0.3,0.1

Type RM Length L Ch R = 1 ,3494.6  ,309,304.5,298.6
XS GIS Cut Line= 2
     1667421.194      587365.747     1667642.026      587595.339
#Sta/Elev= 17
       0     620     9.6  612.14    19.3  605.27      29  601.42    38.6   600.8
    68.9  600.32    83.9   600.1    96.5  599.98   135.2  600.13   164.1  600.61
   193.1  601.34   212.4     602   241.3  603.18     280  605.09   299.2  605.94
   308.9  607.24   318.6  609.99
#Mann= 3 , 0 , 0
       0      .1       0    68.9    .045       0    83.9      .1       0
Bank Sta=68.9,83.9
XS Rating Curve= 0 ,0
Exp/Cntr=0.3,0.1

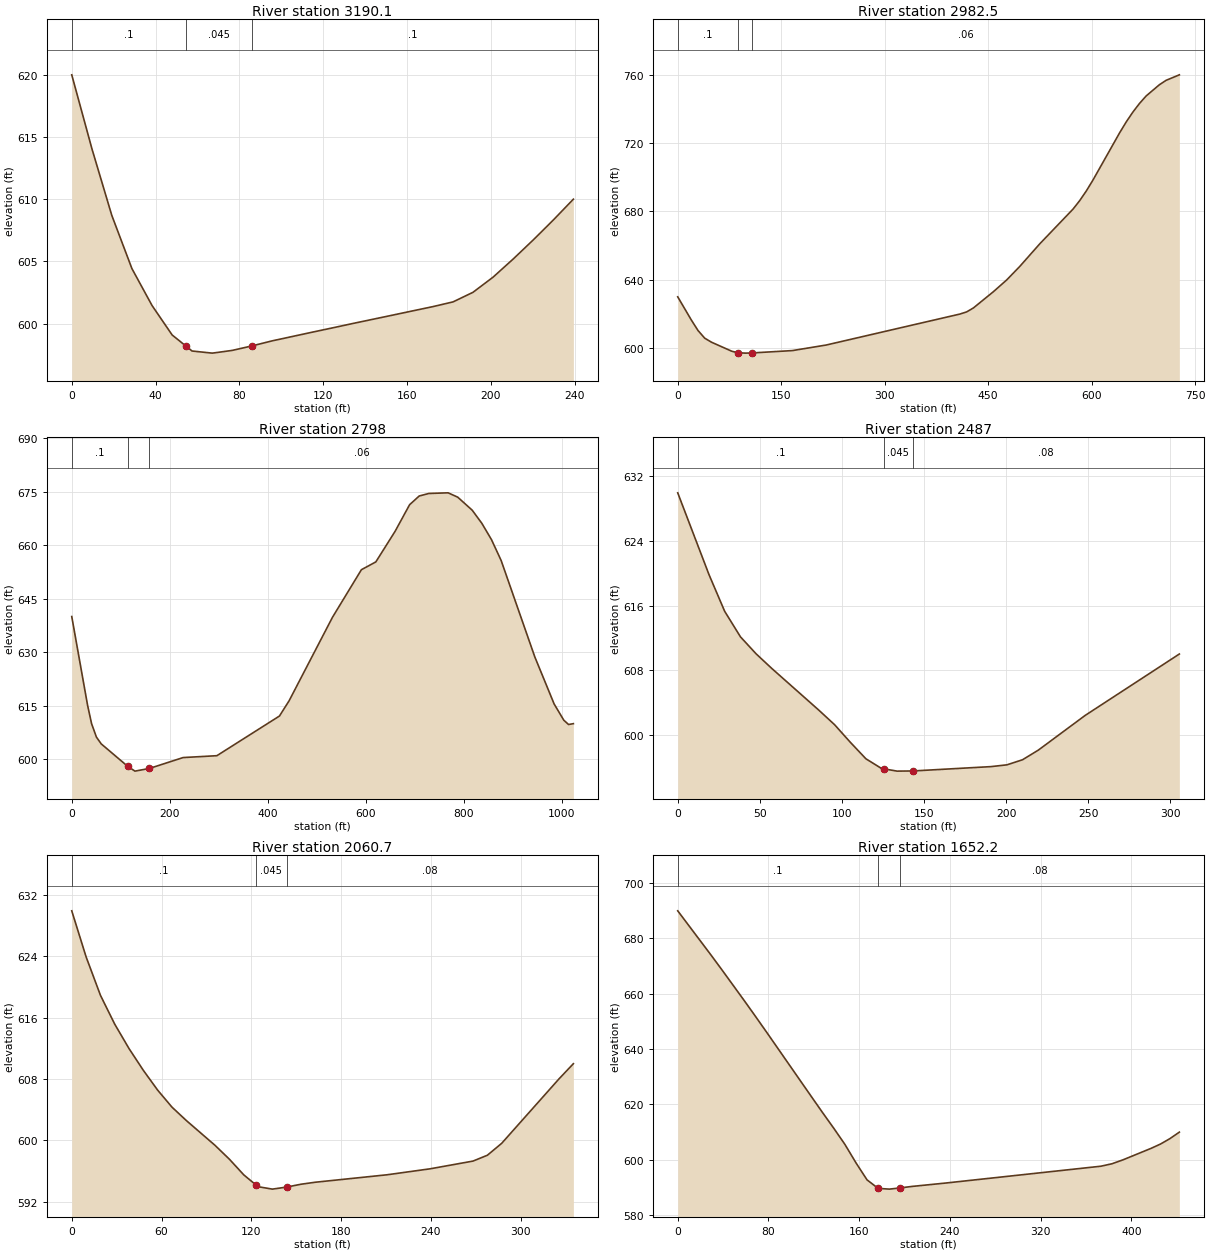
Type RM Length L Ch R = 1 ,3190.1  ,205.5,207.6,209.7
XS GIS Cut Line= 2
     1667237.017      587591.042     1667408.084      587758.365
#Sta/Elev= 28
       0     620     9.6  614.07    19.1   608.7    28.7  604.42    38.3  601.45
    47.9  599.08    54.3  598.21    57.4  597.79      67  597.62    69.3  597.67
    76.6  597.84    86.2  598.21    95.7  598.61   105.3  598.96   114.9  599.31
   124.4  599.65     134     600   143.6  600.34   153.2  600.68   162.7  601.02
   172.3  601.36   181.9  601.74   191.4  602.51     201  603.73   210.6  605.19
   220.2  606.73   229.7  608.32   239.3     610
#Mann= 3 , 0 , 0
       0      .1       0    54.3    .045       0    86.2      .1       0
Bank Sta=54.3,86.2
XS Rating Curve= 0 ,0
Exp/Cntr=0.3,0.1

Type RM Length L Ch R = 1 ,2982.5  ,166.3,184.5,202.1
XS GIS Cut Line= 3
     1667066.864        587702.6     1667272.392      587925.687
     1667671.197      588069.384
#Sta/Elev= 30
       0     630    19.6  616.52    29.4  610.29    39.1   605.8    48.9  603.44
    78.3  598.16    86.7  597.29    97.8  597.04   107.6  597.14   166.3  598.53
   215.3  601.79   409.3  619.94   418.9  621.19   428.6  623.48   457.5  632.97
   476.8  639.85     496  647.86   524.9  661.06   573.1  681.38   582.7  686.31
   592.4  692.04     602   698.4   640.5  725.96   650.2  732.42   659.8  738.16
   669.4  743.22   679.1  747.63   698.3   754.2     708  756.77   727.2  759.99
#Mann= 3 , 0 , 0
       0      .1       0    86.7    .045       0   107.6     .06       0
Bank Sta=86.7,107.6
XS Rating Curve= 0 ,0
Exp/Cntr=0.3,0.1

Type RM Length L Ch R = 1 ,2798    ,311.1,311,311.2
XS GIS Cut Line= 4
     1666958.596      587725.234     1666968.439      587764.541
     1666952.991        588118.3      1667259.05      588668.538
#Sta/Elev= 30
       0     640    32.4   615.1    40.5     610    50.4  606.23    60.2  604.34
     114  598.08     129  596.71   158.6  597.46   227.4  600.51   296.3  601.03
   424.1  612.14   443.8  616.41   532.4   639.8   591.4  653.11   620.9   655.3
   660.2  663.86   689.8  671.31   709.4  673.75   729.1  674.46   768.5  674.64
   788.1  673.42   817.6  669.78   837.3  666.11     857  661.53   876.7   655.7
   945.5  628.68   984.9  615.52  1004.6  610.98  1014.4  609.76  1024.2     610
#Mann= 3 , 0 , 0
       0      .1       0     114    .045       0   158.6     .06       0
Bank Sta=114,158.6
XS Rating Curve= 0 ,0
Exp/Cntr=0.3,0.1

Type RM Length L Ch R = 1 ,2487    ,425.9,426.4,425.9
XS GIS Cut Line= 2
     1666668.234      587719.575     1666652.913      588024.678
#Sta/Elev= 20
       0  629.97    19.1  619.81    28.6  615.29    38.2  612.13    47.7  610.03
    57.3  608.21    85.9  603.05    95.5  601.25     105  599.09   114.6  597.02
   124.1  595.82   125.6  595.77   133.6  595.49   143.2  595.51   190.9  596.05
   200.5  596.27     210   596.9   219.6  598.09   248.2   602.4   305.5     610
#Mann= 3 , 0 , 0
       0      .1       0   125.6    .045       0   143.2     .08       0
Bank Sta=125.6,143.2
XS Rating Curve= 0 ,0
Exp/Cntr=0.3,0.1

Type RM Length L Ch R = 1 ,2060.7  ,407.6,408.4,408
XS GIS Cut Line= 2
     1666247.103        587692.3     1666230.251       588027.15
#Sta/Elev= 25
       0  629.95     9.6  623.94    19.2  618.92    28.7  615.17    38.3  611.97
    47.9  609.12    57.5  606.53      67  604.33    76.6  602.58    95.8  599.34
   105.4  597.53     115  595.49   123.1  594.18   124.5  593.95   134.1  593.63
   143.7   593.9   153.3  594.27   162.8  594.53   210.7   595.5   239.5  596.28
   268.2  597.29   277.8  598.05   287.4  599.61   325.7  608.02   335.3     610
#Mann= 3 , 0 , 0
       0      .1       0   123.1    .045       0   143.7     .08       0
Bank Sta=123.1,143.7
XS Rating Curve= 0 ,0
Exp/Cntr=0.3,0.1

Type RM Length L Ch R = 1 ,1652.2  ,313.1,316.1,318.2
XS GIS Cut Line= 3
     1665907.912      587554.135     1665895.606      587946.683
     1665882.973      587994.585
#Sta/Elev= 25
       0  689.99    29.5  673.93    39.3  668.48    58.9   657.4    68.7  651.76
    78.6  645.99   117.8  622.88   127.6  617.13   137.5  611.45   147.3  605.64
   157.1  598.95   166.9  592.76   176.7  589.67     177  589.66   186.6   589.4
   196.4  589.85   206.2  590.36   235.6  591.57   373.1  597.68   382.9  598.57
   392.7     600   417.5  604.16   425.8  605.72     434  607.66   442.3     610
#Mann= 3 , 0 , 0
       0      .1       0     177    .045       0   196.4     .08       0
Bank Sta=177,196.4
XS Rating Curve= 0 ,0
Exp/Cntr=0.3,0.1

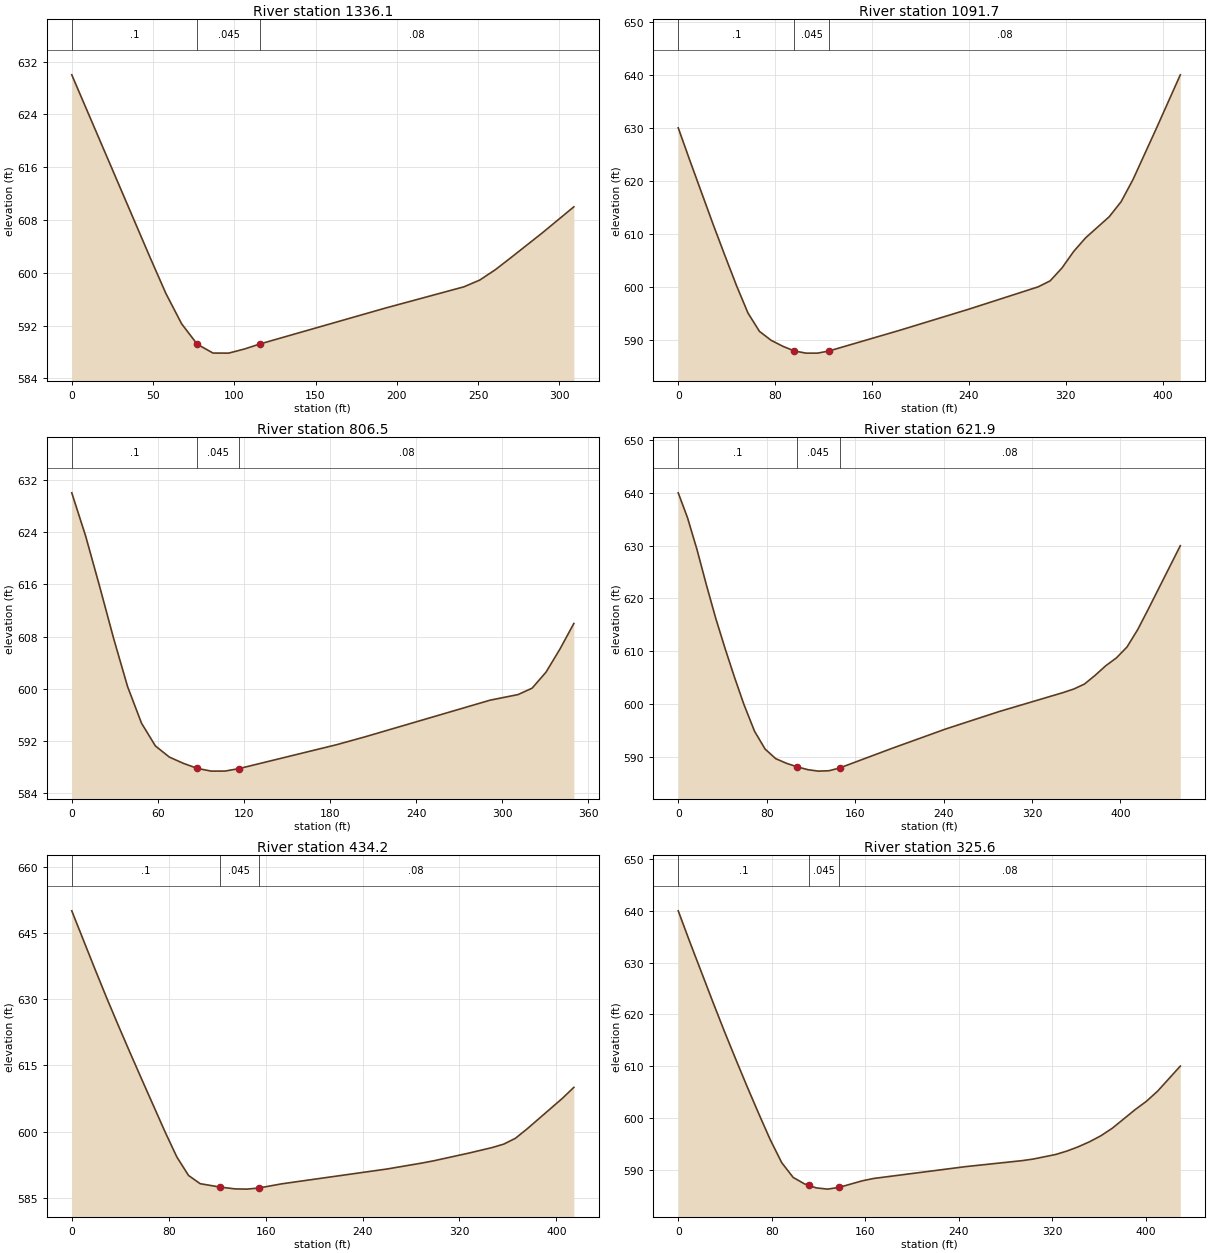
Type RM Length L Ch R = 1 ,1336.1  ,242.4,244.3,245.6
XS GIS Cut Line= 2
     1665605.335      587645.259     1665560.961      587950.913
#Sta/Elev= 16
       0     630    48.3  602.26    57.9  596.88    67.6  592.27    77.2  589.18
    86.9  587.84    96.5  587.83   106.2  588.45   115.8  589.22     193  594.66
   241.3  597.88     251   598.9   260.6  600.47   270.2   602.3   289.6  606.07
   308.9     610
#Mann= 3 , 0 , 0
       0      .1       0    77.2    .045       0   115.8     .08       0
Bank Sta=77.2,115.8
XS Rating Curve= 0 ,0
Exp/Cntr=0.3,0.1

Type RM Length L Ch R = 1 ,1091.7  ,280.8,285.3,289.8
XS GIS Cut Line= 3
     1665375.477       587612.25     1665317.117      587903.784
     1665311.689      588020.902
#Sta/Elev= 25
       0  629.99     9.6  623.83    28.8  611.79    38.4  605.98      48   600.3
    57.6  595.05    67.1  591.59    76.7  589.91    86.3  588.79    95.9   587.9
   105.5  587.49   115.1  587.49   124.4  587.89   182.2  591.75   239.8  595.77
   297.3     600   307.1  601.12   316.9  603.56   326.6  606.69   336.4  609.24
   355.9  613.22   365.7  616.05   375.5  620.22     395  629.97   414.6  639.99
#Mann= 3 , 0 , 0
       0      .1       0    95.9    .045       0   124.4     .08       0
Bank Sta=95.9,124.4
XS Rating Curve= 0 ,0
Exp/Cntr=0.3,0.1

Type RM Length L Ch R = 1 ,806.5   ,183.9,184.5,184.3
XS GIS Cut Line= 2
     1665121.751      587557.812     1664986.162      587880.409
#Sta/Elev= 21
       0  629.99     9.7  623.36    19.4  615.69    29.2  607.69    38.9  600.34
    48.6  594.75    58.3  591.26      68  589.56    77.8   588.6    87.5  587.83
    97.2  587.41   106.9  587.42   116.6   587.8   184.7  591.46   204.1  592.64
   291.6  598.27     311  599.12   320.8   600.1   330.5  602.55   340.2  606.08
   349.9     610
#Mann= 3 , 0 , 0
       0      .1       0    87.5    .045       0   116.6     .08       0
Bank Sta=87.5,116.6
XS Rating Curve= 0 ,0
Exp/Cntr=0.3,0.1

Type RM Length L Ch R = 1 ,621.9   ,187.2,187.7,188.4
XS GIS Cut Line= 3
     1664943.803      587456.166     1664940.884      587515.413
     1664785.026      587878.097
#Sta/Elev= 30
       0  640.01     8.5  635.23      17  629.24    25.4  622.63    33.9  616.27
    42.4  610.52    50.8  605.14    59.3     600      69  594.87    78.6  591.48
    88.2  589.67    97.8   588.8   107.5  588.13   117.3  587.58   126.7  587.31
   136.3  587.38     146  587.91   194.1  591.68   242.2  595.31   290.4   598.6
   348.2  602.19   357.8  602.86   367.4   603.8     377  605.44   386.7  607.27
   396.3  608.75   405.9  610.82   415.6  614.12   425.2  618.01   454.1     630
#Mann= 3 , 0 , 0
       0      .1       0   107.5    .045       0     146     .08       0
Bank Sta=107.5,146
XS Rating Curve= 0 ,0
Exp/Cntr=0.3,0.1

Type RM Length L Ch R = 1 ,434.2   ,109.2,108.7,108.2
XS GIS Cut Line= 2
     1664799.586       587378.01     1664625.924      587754.264
#Sta/Elev= 25
       0  649.99    19.3  636.68    28.9  630.21    38.6  623.91    48.2   617.8
    57.8   611.8    77.1  599.86    86.7  594.25    96.4  590.04     106  588.18
   122.5  587.41   134.9     587   144.6  586.95   154.2   587.2   173.5  588.16
   260.2  591.51   289.1  592.86   298.8  593.37   327.7  595.11   346.9  596.36
   356.6  597.15   366.2  598.47   375.8  600.59   404.8  607.48   414.4     610
#Mann= 3 , 0 , 0
       0      .1       0   122.5    .045       0   154.2     .08       0
Bank Sta=122.5,154.2
XS Rating Curve= 0 ,0
Exp/Cntr=0.3,0.1

Type RM Length L Ch R = 1 ,325.6   ,324.6,325.6,326.6
XS GIS Cut Line= 3
     1664694.326      587344.484     1664603.729      587551.672
     1664586.554      587754.232
#Sta/Elev= 30
       0     640     9.8  634.05    29.5  622.46    39.3  616.81    49.2  611.32
      59  605.99    68.8  600.83    78.6  595.82    88.5  591.34    98.3  588.48
   108.2  587.21   111.6  586.95     118  586.46   127.8  586.22   137.6  586.56
   157.3  587.82   167.1  588.28   245.5  590.56   293.9  591.72   303.6  592.03
   322.9  592.92   332.6  593.59   342.3  594.42     352   595.4   361.6  596.55
   371.3     598   390.7  601.57   400.4  603.19   410.1  605.18   429.4     610
#Mann= 3 , 0 , 0
       0      .1       0   111.6    .045       0   137.6     .08       0
Bank Sta=111.6,137.6
XS Rating Curve= 0 ,0
Exp/Cntr=0.3,0.1

Chan Stop Cuts=-1
Use User Specified Reach Order=0
Composite Channel Slope=5